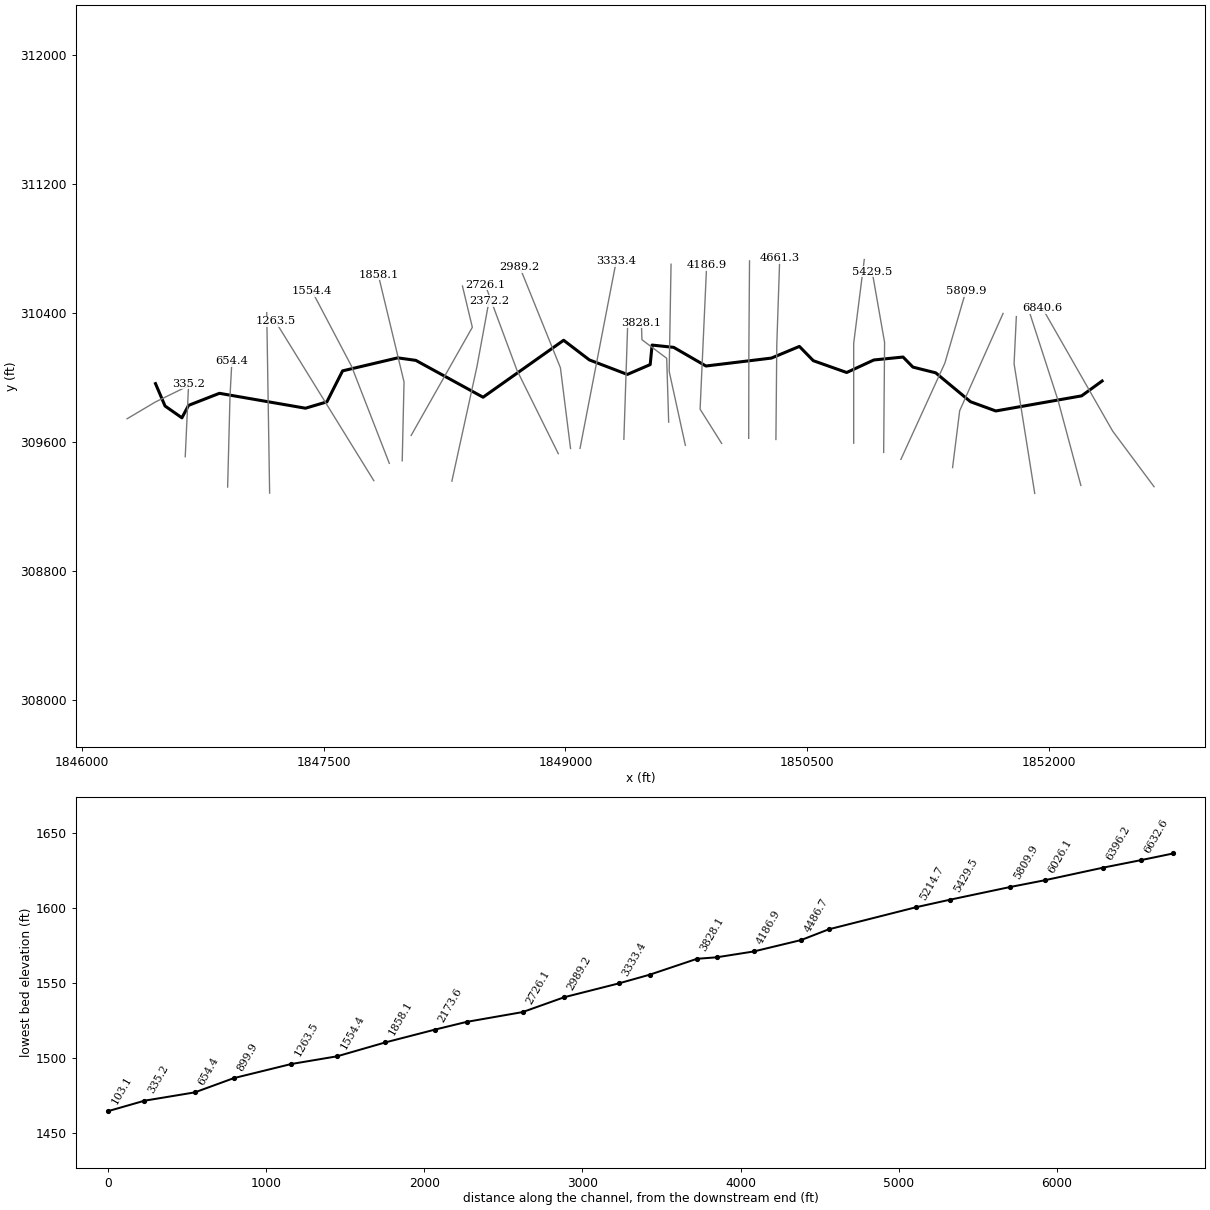
--- RghtHndFrk.prj (project) ---

Proj Title=RghtHndFrk
Current Plan=p01
Default Exp/Contr=0,0
English Units
Geom File=g01
Flow File=f01
Plan File=p01
BEGIN DESCRIPTION:
END DESCRIPTION:
DSS Export Rating Curves= 0
DSS Export Rating Curve Sorted= 0
DSS Export Volume Flow Curves= 0
DXF OffsetX= 0
DXF OffsetY= 0
DXF ScaleX= 0
DXF ScaleY= 0

--- RghtHndFrk.p01 (plan) ---

Plan Title=Floodplain
Program Version=4.00
Geom File=g01
Flow File=f01
K Sum by GR=0
Std Step Tol=0.01
Critical Tol=0.01
Num of Std Step Trials=20
Max Error Tol=0.3
Flow Tol Ratio=0.001
Split Flow NTrial=30
Split Flow Tol=0.02
Split Flow Ratio=0.02
Log Output Level=0
Friction Slope Method=1
Unsteady Friction Slope Method=2
Unsteady Bridges Friction Slope Method=1
Global Log Level=0
CheckData=False
Run HTab=0
Run UNet=0
Run PostProcess=0
UNET Theta=0
UNET Theta Warmup=0
UNET ZTol=0
UNET ZSATol=0
UNET MxIter=0
UNET MaxInSteps=0
UNET DtIC=0
UNET DtMin=0
UNET MaxCRTS=0
UNET WFStab=0
UNET SFStab=0
UNET WFX=0
UNET SFX=0
UNET DSS MLevel=0
UNET DZMax Abort=0
UNET Convert EG Bridges=0
UNET Use Existing IB Tables=0
UNET Froude Limit=0
UNET Froude Power=0
Write IC File=0
Echo Input=False
Echo Output=False
Write Detailed=0

--- RghtHndFrk.f01 (steady flow) ---

Flow Title=NFF Regression Equation
Program Version=4.00
Number of Profiles=1
Profile Names=P100yr
River Rch & RM=RghtHndFrk,Main      ,6840.6
824.6661
River Rch & RM=RghtHndFrk,Main      ,6632.6
891.6806
River Rch & RM=RghtHndFrk,Main      ,4661.3
959.2291
River Rch & RM=RghtHndFrk,Main      ,4186.9
1060.589
River Rch & RM=RghtHndFrk,Main      ,335.2
1130.957
Boundary for River Rch & Prof#=RghtHndFrk,Main      ,1
Up Type=0
Dn Type=3
Dn Slope=0.02749

--- RghtHndFrk.g01 (geometry) ---

Geom Title=USGS 3m DEM
Program Version=4.10

River Reach=RghtHndFrk      ,Main
Reach XY= 30
     1852331.107      309978.427     1852203.857      309886.192
     1851671.128      309792.428     1851514.198      309849.659
      1851298.12      310029.164     1851156.646       310064.67
      1851095.43      310127.192     1850914.381      310108.963
     1850745.583      310031.118     1850538.407      310104.492
     1850451.944      310193.078     1850278.358      310120.678
      1849871.81      310071.463      1849671.79      310187.154
     1849537.632      310201.486     1849525.905      310080.353
      1849383.93       310019.14     1849148.393      310109.243
     1848988.525      310231.276     1848488.385      309877.774
     1848071.005      310106.451      1847958.99      310122.085
     1847616.427      310041.341     1847518.947      309848.877
     1847385.876      309809.502     1846851.851      309901.999
     1846660.164      309827.112     1846619.077      309749.957
     1846514.377      309823.173     1846455.088      309962.147

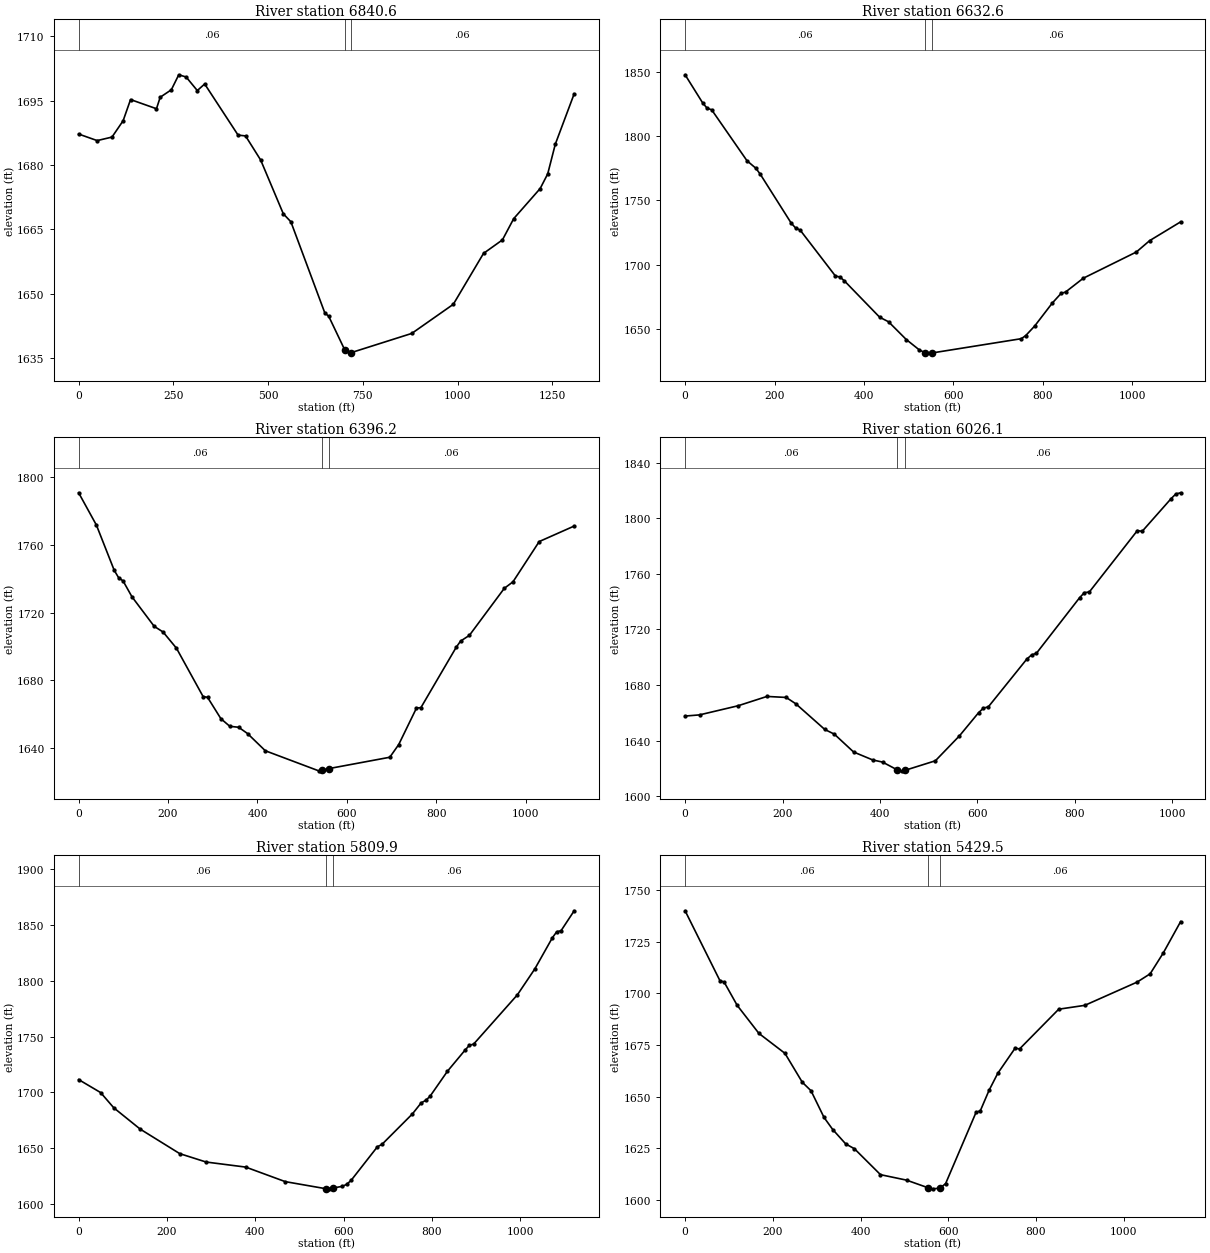
Type RM Length L Ch R = 1 ,6840.6  ,213.7,207.9,203.3
XS GIS Cut Line= 3
     1852653.568      309322.127     1852396.517      309667.421
     1851961.333      310428.873
#Sta/Elev= 30
       0  1687.2    48.9 1685.67      88 1686.49   117.4  1690.3     137 1695.24
   205.4  1693.1   215.2 1695.78   244.6 1697.52   264.2 1701.02   283.7  1700.5
   313.1 1697.34   332.6 1698.87   420.7 1686.95   440.4 1686.76   480.3 1681.14
   540.1 1668.59     560 1666.74   649.7 1645.45   659.7 1644.73   702.4 1636.81
   717.4 1636.17     879  1640.7   988.6 1647.49  1068.3 1659.36  1118.2 1662.51
    1148 1667.47  1217.8 1674.49  1237.7 1677.91  1257.7 1684.83  1307.5 1696.58
#Mann= 3 , 0 , 0
       0     .06       0   702.4    .045       0   717.4     .06       0
Bank Sta=702.4,717.4
XS Rating Curve= 0 ,0
Exp/Cntr=0.3,0.1

Type RM Length L Ch R = 1 ,6632.6  ,238.7,236.4,232.9
XS GIS Cut Line= 3
     1852199.191      309330.029     1852058.313       309855.28
     1851884.552      310391.814
#Sta/Elev= 30
       0 1847.61    39.6  1825.6    49.4 1821.58    59.3 1820.46   138.4 1780.83
   158.2 1775.01   168.1 1770.35   237.3 1732.35   247.2 1728.56   257.1 1727.03
   336.2 1691.24   346.1 1690.57     356 1687.58     435 1659.29   454.8 1655.78
   494.4    1642     524 1633.81   536.3  1631.8   551.3 1631.65   553.7 1631.64
   751.6 1642.63   761.5 1645.06   781.3 1652.38   820.8 1670.27   840.6 1677.83
   850.5 1678.86   890.1 1689.58  1008.8 1709.95  1038.5 1718.77  1107.8 1733.38
#Mann= 3 , 0 , 0
       0     .06       0   536.3    .045       0   551.3     .06       0
Bank Sta=536.3,551.3
XS Rating Curve= 0 ,0
Exp/Cntr=0.3,0.1

Type RM Length L Ch R = 1 ,6396.2  ,383,369.9,356.8
XS GIS Cut Line= 3
     1851912.897      309280.401      1851784.58      310085.609
     1851798.641      310378.298
#Sta/Elev= 30
       0 1790.57    39.8 1771.51    79.6 1744.88    89.5  1740.5    99.4 1738.62
   119.3 1729.27     169 1711.87   188.9 1708.52   218.8 1698.98   278.4 1670.48
   288.4 1670.01   318.2 1657.43   338.1 1652.95     358 1652.37   377.8 1648.67
   417.6 1638.53     537  1626.7   543.9 1626.99   558.9 1627.98     696 1634.71
   715.9 1642.17   755.7 1663.71   765.6 1663.95   844.7 1699.59   854.4 1703.18
     874 1706.53   952.1 1734.25   971.6 1738.12  1030.2 1761.82  1108.4 1770.96
#Mann= 3 , 0 , 0
       0     .06       0   543.9    .045       0   558.9     .06       0
Bank Sta=543.9,558.9
XS Rating Curve= 0 ,0
Exp/Cntr=0.3,0.1

Type RM Length L Ch R = 1 ,6026.1  ,215.7,215.9,216.1
XS GIS Cut Line= 3
     1851402.839      309441.062      1851446.96      309794.028
     1851716.313      310397.909
#Sta/Elev= 30
       0 1657.68    29.6 1658.52   108.7 1665.08     168 1671.79   207.5 1671.06
   227.3 1666.47   286.6 1648.05   306.3 1644.66   345.8 1631.83   385.3 1626.08
   405.1  1624.6   435.4 1618.98   444.5 1618.29   450.4 1618.56   513.6 1625.52
     563 1643.45   602.4 1660.16   612.3 1663.41   622.2 1664.27   701.1 1698.59
     711 1701.64   720.9  1702.8   809.7 1742.85   819.6 1746.49   829.4 1746.84
   928.1 1791.04     938 1790.52   997.2 1813.97  1007.1 1817.39  1016.9 1818.23
#Mann= 3 , 0 , 0
       0     .06       0   435.4    .045       0   450.4     .06       0
Bank Sta=435.4,450.4
XS Rating Curve= 0 ,0
Exp/Cntr=0.3,0.1

Type RM Length L Ch R = 1 ,5809.9  ,370.8,380.6,390.4
XS GIS Cut Line= 3
     1851082.076       309491.92     1851354.882      310089.446
     1851485.205      310535.851
#Sta/Elev= 30
       0 1711.51    49.8  1699.9    79.6 1686.26   139.3 1667.26   228.9 1645.32
   288.6 1637.82   378.2  1633.3   467.8  1620.3   560.4 1613.92   567.3 1613.86
   575.4 1614.57   597.1  1616.1   607.1 1617.93     617 1621.48   676.6 1651.55
   686.5 1653.49   755.8 1680.88   775.6 1690.73   785.5 1692.84   795.4 1696.48
     835 1718.96   874.5 1737.68   884.4 1742.07   894.3 1743.24   993.3 1787.24
  1032.8 1810.41  1072.4 1838.16  1082.3 1843.58  1092.2 1844.56  1121.9 1862.37
#Mann= 3 , 0 , 0
       0     .06       0   560.4    .045       0   575.4     .06       0
Bank Sta=560.4,575.4
XS Rating Curve= 0 ,0
Exp/Cntr=0.3,0.1

Type RM Length L Ch R = 1 ,5429.5  ,215.4,214.5,213.7
XS GIS Cut Line= 3
     1850975.059      309535.058     1850980.814      310217.972
      1850903.48      310657.854
#Sta/Elev= 30
       0 1739.99    79.2 1706.24    89.1 1705.44   118.8 1694.19   168.3 1680.63
   227.6 1670.99   267.2 1656.98     287 1652.89   316.7 1639.96   336.5 1634.12
   366.2 1627.13     386 1624.81   445.4 1612.26   504.8 1609.61   554.3 1605.89
   564.2  1605.4   581.3 1605.73   593.9 1607.96   663.1 1642.36     673  1643.2
   692.9 1653.09   712.7  1661.3   752.4 1673.53   762.3 1673.09   851.7 1692.35
   911.2 1694.22  1030.3 1705.46  1060.1 1709.48  1089.9 1719.53  1129.6 1734.76
#Mann= 3 , 0 , 0
       0     .06       0   554.3    .045       0   581.3     .06       0
Bank Sta=554.3,581.3
XS Rating Curve= 0 ,0
Exp/Cntr=0.3,0.1

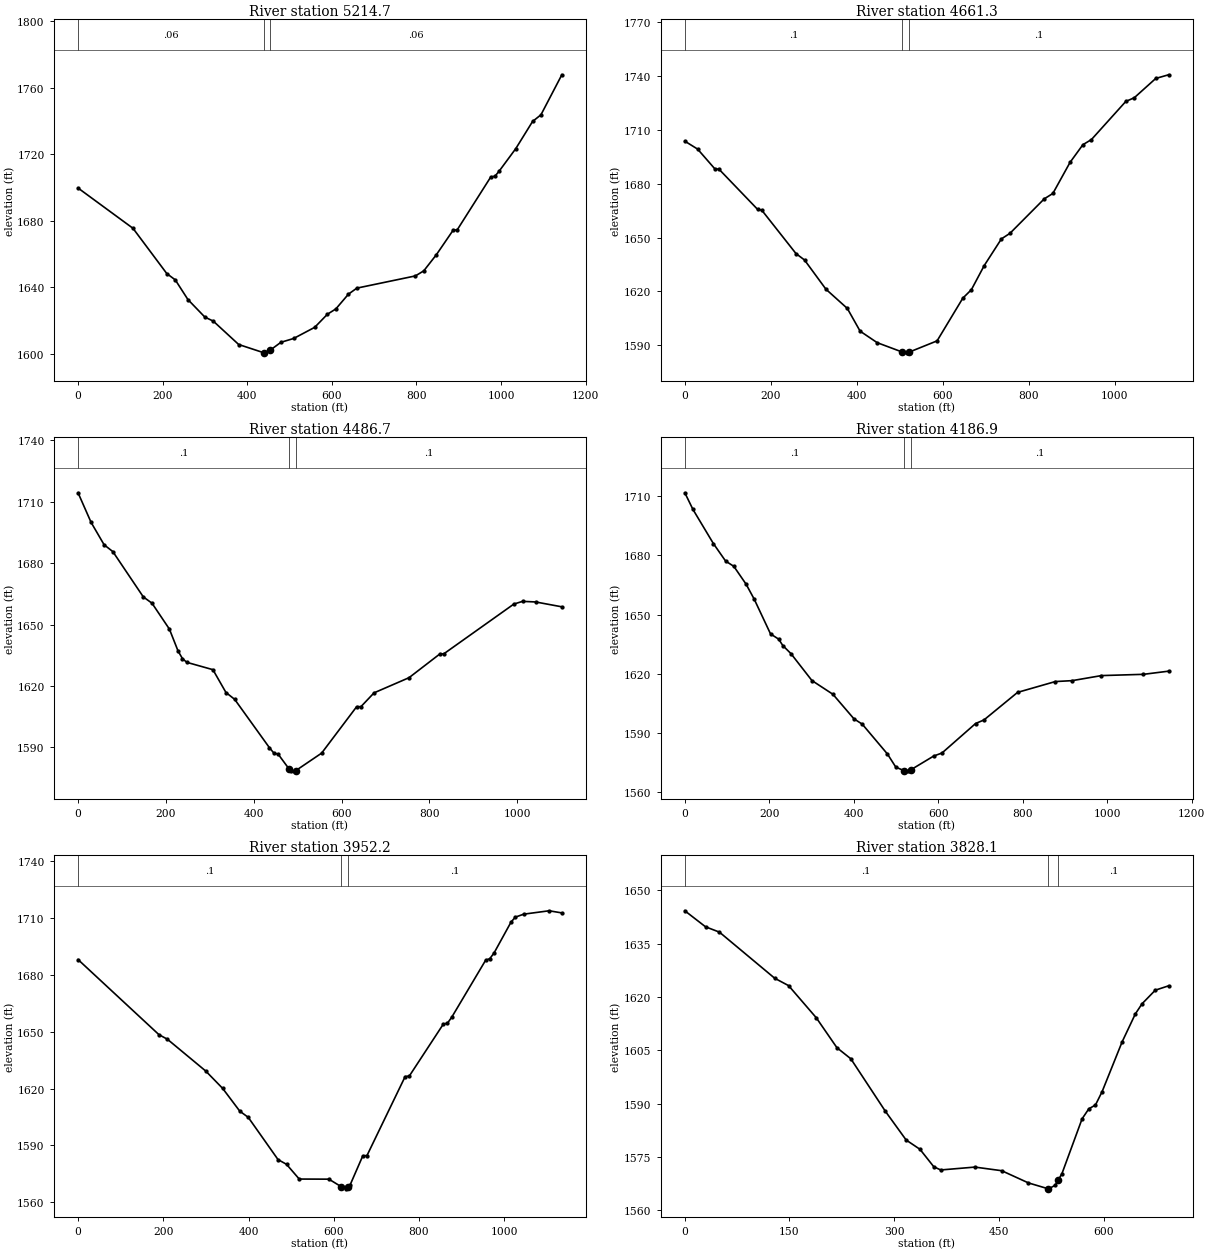
Type RM Length L Ch R = 1 ,5214.7  ,552.5,553.3,554.2
XS GIS Cut Line= 3
     1850788.985      309592.607     1850788.985      310212.217
     1850854.688      310732.406
#Sta/Elev= 30
       0 1699.66   129.9  1675.4   209.9 1648.12   229.9 1644.34   259.8 1632.49
   299.8 1621.94   319.8 1619.49   379.8 1605.42   439.2 1600.45   439.7  1600.4
   454.2 1601.99   479.7 1606.75   509.7 1609.04   559.6 1615.77   589.6 1623.64
   609.6 1626.86   639.4 1635.76   659.2 1639.37   797.7 1646.73   817.5  1649.8
   847.2 1659.48   886.7  1674.2   896.6  1674.5   975.8  1706.3   985.6 1706.73
   995.5 1709.77  1035.1 1723.44  1074.7 1739.74  1094.5 1743.76  1143.9 1767.86
#Mann= 3 , 0 , 0
       0     .06       0   439.2    .045       0   454.2     .06       0
Bank Sta=439.2,454.2
XS Rating Curve= 0 ,0
Exp/Cntr=0.3,0.1

Type RM Length L Ch R = 1 ,4661.3  ,174.3,174.6,174.8
XS GIS Cut Line= 3
      1850306.25      309615.433     1850311.651       310202.13
     1850329.912      310740.332
#Sta/Elev= 30
       0 1703.76    29.8 1699.33    69.6 1688.38    79.6 1688.09   169.1 1665.75
     179 1665.25   258.6 1641.03   278.4 1637.46   328.2 1621.16   377.9 1610.45
   407.7 1597.75   447.5 1591.32   506.2 1586.06   517.1 1585.66   521.2 1586.01
   586.7 1592.34   646.6 1616.18   666.5 1620.89   696.4 1634.38   736.3 1649.24
   756.2 1652.34     836 1671.59     856 1674.59   895.9 1691.91   925.8 1701.78
   945.7 1704.66  1025.5  1725.9  1045.4    1728  1095.3 1738.76  1125.2  1740.8
#Mann= 3 , 0 , 0
       0      .1       0   506.2    .045       0   521.2      .1       0
Bank Sta=506.2,521.2
XS Rating Curve= 0 ,0
Exp/Cntr=0.3,0.1

Type RM Length L Ch R = 1 ,4486.7  ,300.7,299.9,299
XS GIS Cut Line= 3
     1850137.341      309622.431     1850138.368      310177.154
     1850142.442       310723.96
#Sta/Elev= 30
       0 1714.42    29.7 1699.95    59.4 1688.99    79.2 1685.68   148.6 1663.53
   168.4 1660.45     208  1647.8   227.8 1637.05   237.7  1633.4   247.6 1631.55
   307.1 1627.96   336.8  1616.8   356.6 1613.47   435.8 1589.82   445.8 1587.22
   455.7 1586.66   480.4 1579.47   485.4 1578.52   495.4 1578.57   554.7 1587.19
   634.3 1609.85   644.2  1609.9     674 1616.64   753.6 1624.04   823.2 1635.54
   833.1 1635.75   992.2 1660.01  1012.1 1661.35  1041.9 1661.06  1101.6 1658.68
#Mann= 3 , 0 , 0
       0      .1       0   480.4    .045       0   495.4      .1       0
Bank Sta=480.4,495.4
XS Rating Curve= 0 ,0
Exp/Cntr=0.3,0.1

Type RM Length L Ch R = 1 ,4186.9  ,233.9,234.6,235.3
XS GIS Cut Line= 3
     1849969.338      309590.917     1849835.591       309803.62
      1849876.24      310696.709
#Sta/Elev= 30
       0 1711.63    19.3 1703.17    67.6 1685.94    96.6 1677.06     116 1674.41
     145 1665.39   164.3 1657.78   202.9 1640.22   222.3 1637.54   231.9 1634.34
   251.3 1630.22   300.9 1616.61   350.6 1609.66   400.3 1597.26   420.1 1594.53
   479.7 1579.43   499.6 1572.76   519.3 1570.99   529.4 1570.92   534.3 1571.35
     589 1578.39   608.9 1579.96   688.3 1594.86   708.2 1596.68   787.7 1610.62
   877.1  1616.1   916.8 1616.56   986.3 1619.12  1085.7 1619.76  1145.3 1621.36
#Mann= 3 , 0 , 0
       0      .1       0   519.3    .045       0   534.3      .1       0
Bank Sta=519.3,534.3
XS Rating Curve= 0 ,0
Exp/Cntr=0.3,0.1

Type RM Length L Ch R = 1 ,3952.2  ,98.7,123.5,146.8
XS GIS Cut Line= 3
     1849744.091      309579.283     1849643.762      310037.652
     1849655.272      310703.301
#Sta/Elev= 30
       0  1688.1   189.7 1648.46   209.6 1646.03   299.5 1629.25   339.4 1620.03
   379.4 1608.06   399.3 1604.78   469.2 1582.47   489.1 1579.98   518.9  1572.2
   588.5 1572.14   617.2  1568.2   628.2 1567.03   632.2 1567.83   638.1    1569
     668 1584.45   677.9 1584.63   767.3 1626.28   777.2 1626.61   856.8 1653.97
   866.7 1654.53   876.6 1657.62   956.1 1687.71     966 1688.58     976 1691.59
  1015.7 1707.85  1025.7 1710.48  1045.5 1712.07  1105.2 1713.86    1135 1712.73
#Mann= 3 , 0 , 0
       0      .1       0   617.2    .045       0   632.2      .1       0
Bank Sta=617.2,632.2
XS Rating Curve= 0 ,0
Exp/Cntr=0.3,0.1

Type RM Length L Ch R = 1 ,3828.1  ,321.8,298.4,275.8
XS GIS Cut Line= 4
     1849640.541      309723.062     1849628.321      310119.334
       1849474.7      310234.549     1849471.209      310339.291
#Sta/Elev= 30
       0 1644.28    29.7 1639.77    49.6 1638.27   128.8  1625.3   148.7 1623.22
   188.3  1614.2     218 1605.75   237.9 1602.64   287.4 1587.87   317.2 1579.78
     337 1577.17   356.8 1572.26   366.7 1571.36   415.7 1572.17   454.1 1571.15
   492.5 1567.71   519.8 1566.12   521.3 1566.05   530.9 1567.07   534.8 1568.41
   540.5 1570.36   569.3 1585.75   578.9 1588.55   588.5 1589.65     598  1593.4
   626.6 1607.37   645.6 1615.26   655.2 1618.11   674.2 1621.94   693.3 1623.17
#Mann= 3 , 0 , 0
       0      .1       0   519.8    .045       0   534.8      .1       0
Bank Sta=519.8,534.8
XS Rating Curve= 0 ,0
Exp/Cntr=0.3,0.1

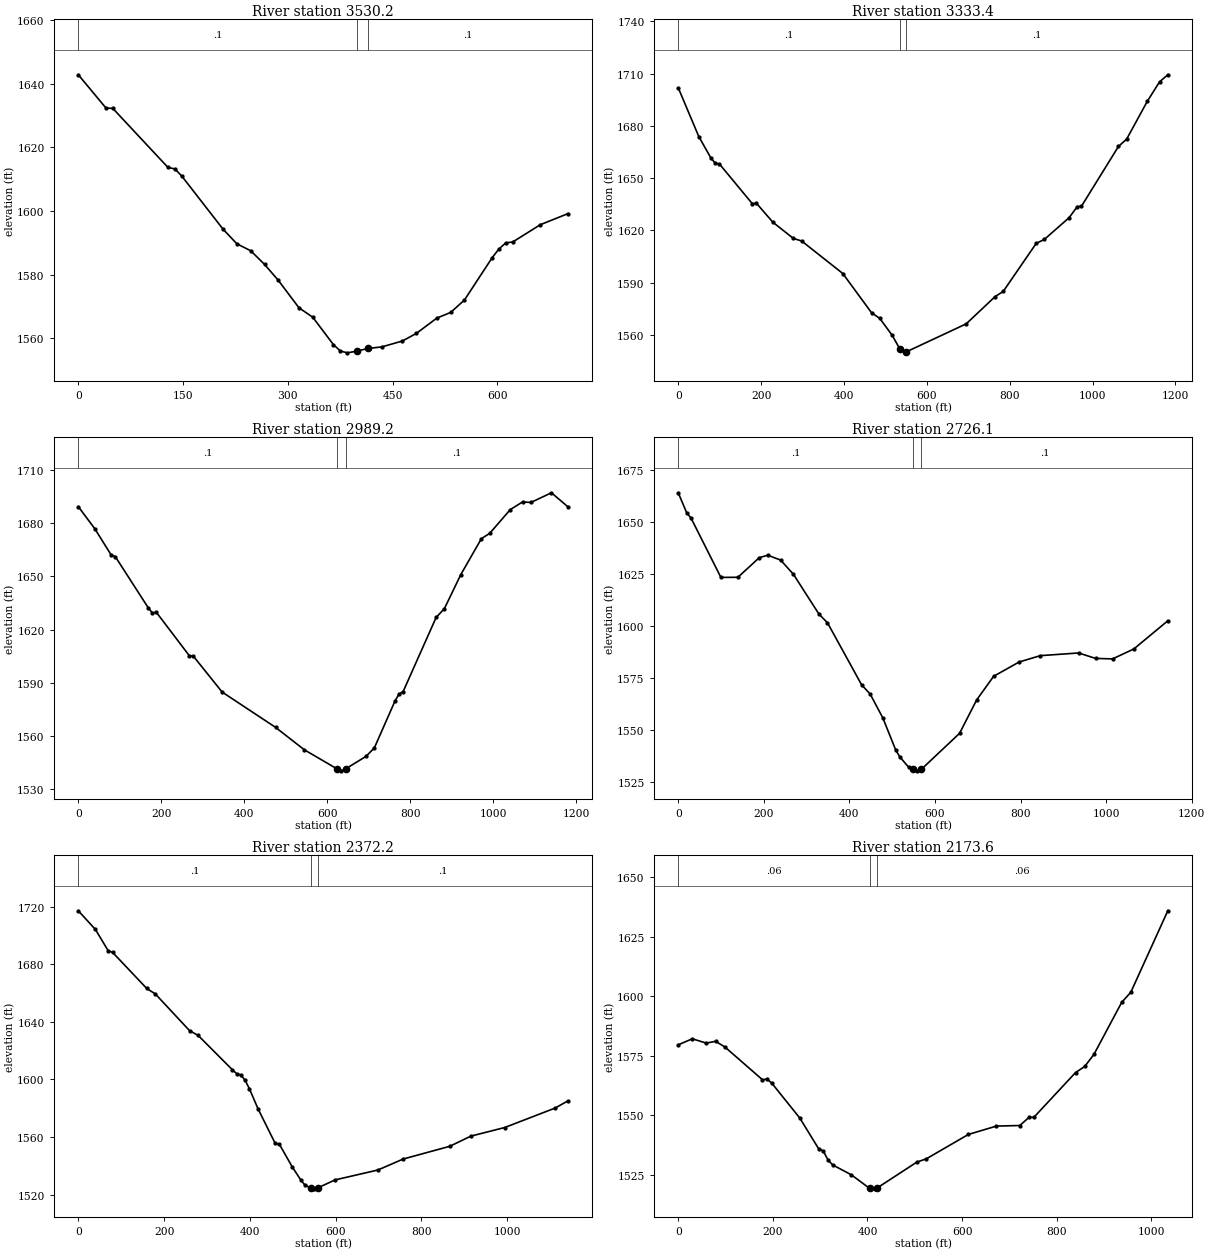
Type RM Length L Ch R = 1 ,3530.2  ,200.9,196.8,192.7
XS GIS Cut Line= 2
     1849362.394      309616.284      1849385.67      310316.888
#Sta/Elev= 30
       0 1642.75    39.5 1632.33    49.4 1632.19   128.4 1613.66   138.2 1613.22
   148.1 1610.97   207.3 1594.27   227.1 1589.69   246.8 1587.53   266.6 1583.25
   286.3 1578.25   315.9 1569.63   335.7 1566.66   365.3 1558.05   375.2 1556.08
     385 1555.49   399.4 1556.03   414.4 1556.87   434.4 1557.34     464 1559.21
   483.8 1561.56   513.4  1566.4   533.2 1568.18   552.9 1572.07   592.4  1585.3
   602.3 1588.11   612.1    1590     622 1590.28   661.5  1595.7     701 1599.17
#Mann= 3 , 0 , 0
       0      .1       0   399.4    .045       0   414.4      .1       0
Bank Sta=399.4,414.4
XS Rating Curve= 0 ,0
Exp/Cntr=0.3,0.1

Type RM Length L Ch R = 1 ,3333.4  ,330.9,344,357
XS GIS Cut Line= 2
     1849090.351      309560.446     1849314.621      310720.699
#Sta/Elev= 30
       0 1701.81    49.6 1673.83    79.4 1661.28    89.4 1658.56    99.3 1658.11
   178.8 1635.28   188.7 1635.55   228.4 1624.64     278 1615.33   297.9 1613.86
   397.2  1595.2   466.7 1572.65   486.6  1569.4   516.4 1559.73   534.4 1552.09
   546.2 1549.66   549.4 1550.11   695.1  1566.3   764.6  1581.9   784.5 1584.93
     864 1612.47   883.8 1614.79   943.4 1627.23   963.3 1633.62   973.2 1633.79
  1062.6 1668.14  1082.4 1672.35  1132.1 1694.02  1161.9 1705.26  1181.7 1709.28
#Mann= 3 , 0 , 0
       0      .1       0   534.4    .045       0   549.4      .1       0
Bank Sta=534.4,549.4
XS Rating Curve= 0 ,0
Exp/Cntr=0.3,0.1

Type RM Length L Ch R = 1 ,2989.2  ,261.5,263.2,262.5
XS GIS Cut Line= 3
     1849031.361       309559.65     1848968.521      310060.671
     1848715.791       310686.41
#Sta/Elev= 30
       0 1689.12    39.6 1676.74    79.2 1661.92    89.1 1661.02   168.3 1632.29
   178.2 1629.37   188.1 1629.66   267.3 1605.31   277.2    1605   346.5 1584.82
   475.2 1564.96   544.6 1552.32     624 1541.51     634 1540.48   644.8 1541.68
   693.5 1548.66   713.4 1553.42     763 1579.72   772.9 1583.73   782.8 1585.12
   862.2 1626.78   882.1 1631.73   921.8 1650.95   971.4 1671.15   991.2 1674.07
  1040.9 1687.46  1070.6  1691.8  1090.5 1691.48  1140.1 1696.94  1179.8 1689.06
#Mann= 3 , 0 , 0
       0      .1       0     624    .045       0   644.8      .1       0
Bank Sta=624,644.8
XS Rating Curve= 0 ,0
Exp/Cntr=0.3,0.1

Type RM Length L Ch R = 1 ,2726.1  ,369.5,353.7,340.3
XS GIS Cut Line= 3
     1848955.275      309527.433     1848698.707      310045.452
     1848501.576      310576.085
#Sta/Elev= 30
       0 1664.11    19.9 1654.43    29.9 1651.96    99.7 1623.47   139.5 1623.53
   189.4 1632.96   209.3 1634.13   239.2  1631.8   269.1    1625   328.9 1605.84
   348.8 1601.68   428.6 1571.87   448.5 1567.49   478.4 1555.89   508.3 1540.55
   518.3 1537.16   538.2  1532.4   548.2 1531.65   558.1 1530.59   568.1 1531.31
   657.5 1548.61   697.2 1564.57     737 1575.97   796.6 1582.85   846.2  1585.9
   935.6 1587.19   975.3 1584.58    1015 1584.34  1064.7 1589.11  1144.1 1602.64
#Mann= 3 , 0 , 0
       0      .1       0   548.2    .045       0   568.1      .1       0
Bank Sta=548.2,568.1
XS Rating Curve= 0 ,0
Exp/Cntr=0.3,0.1

Type RM Length L Ch R = 1 ,2372.2  ,205.8,198.4,191.1
XS GIS Cut Line= 3
      1848294.84       309356.78     1848450.582      310068.345
     1848525.395      310475.023
#Sta/Elev= 30
       0 1717.06    39.9 1704.07    69.8 1689.24    79.8 1688.23   159.6 1663.12
   179.6 1659.34   259.4 1633.88   279.4 1630.55   359.2 1606.75   369.2 1604.01
   379.2  1603.1   389.2 1599.28   399.1 1593.47   419.1 1579.63     459 1555.71
     469 1554.98   498.9 1539.32   518.9  1530.2   528.8 1526.55   543.7 1524.38
   548.8 1524.07   558.7 1524.76   598.7 1530.26   698.5 1537.12   757.9 1544.78
   866.2 1553.58   915.5 1560.65   994.2  1566.6  1112.4 1580.17  1141.9 1585.12
#Mann= 3 , 0 , 0
       0      .1       0   543.7    .045       0   558.7      .1       0
Bank Sta=543.7,558.7
XS Rating Curve= 0 ,0
Exp/Cntr=0.3,0.1

Type RM Length L Ch R = 1 ,2173.6  ,298.5,315.6,332.7
XS GIS Cut Line= 3
     1848041.984      309640.564     1848421.807      310311.968
     1848360.367      310568.091
#Sta/Elev= 30
       0 1579.57    29.7  1582.1    59.3 1580.29    79.1 1581.05    98.9 1578.61
     178 1564.89   187.9 1565.11   197.8 1563.43   257.1 1548.72   296.7 1535.87
   306.6  1534.9   316.5 1531.17   326.4 1529.05   365.9 1524.88   404.5 1519.18
   415.4 1518.98   419.5 1519.22   504.4 1530.24   524.2 1531.59   613.2 1541.86
   672.5 1545.38     722 1545.62   741.7 1549.11   751.6 1549.04   839.7 1567.88
   859.2 1570.46   878.7 1575.55   937.2 1597.38   956.7 1601.73  1034.8 1635.96
#Mann= 3 , 0 , 0
       0     .06       0   404.5    .045       0   419.5     .06       0
Bank Sta=404.5,419.5
XS Rating Curve= 0 ,0
Exp/Cntr=0.3,0.1

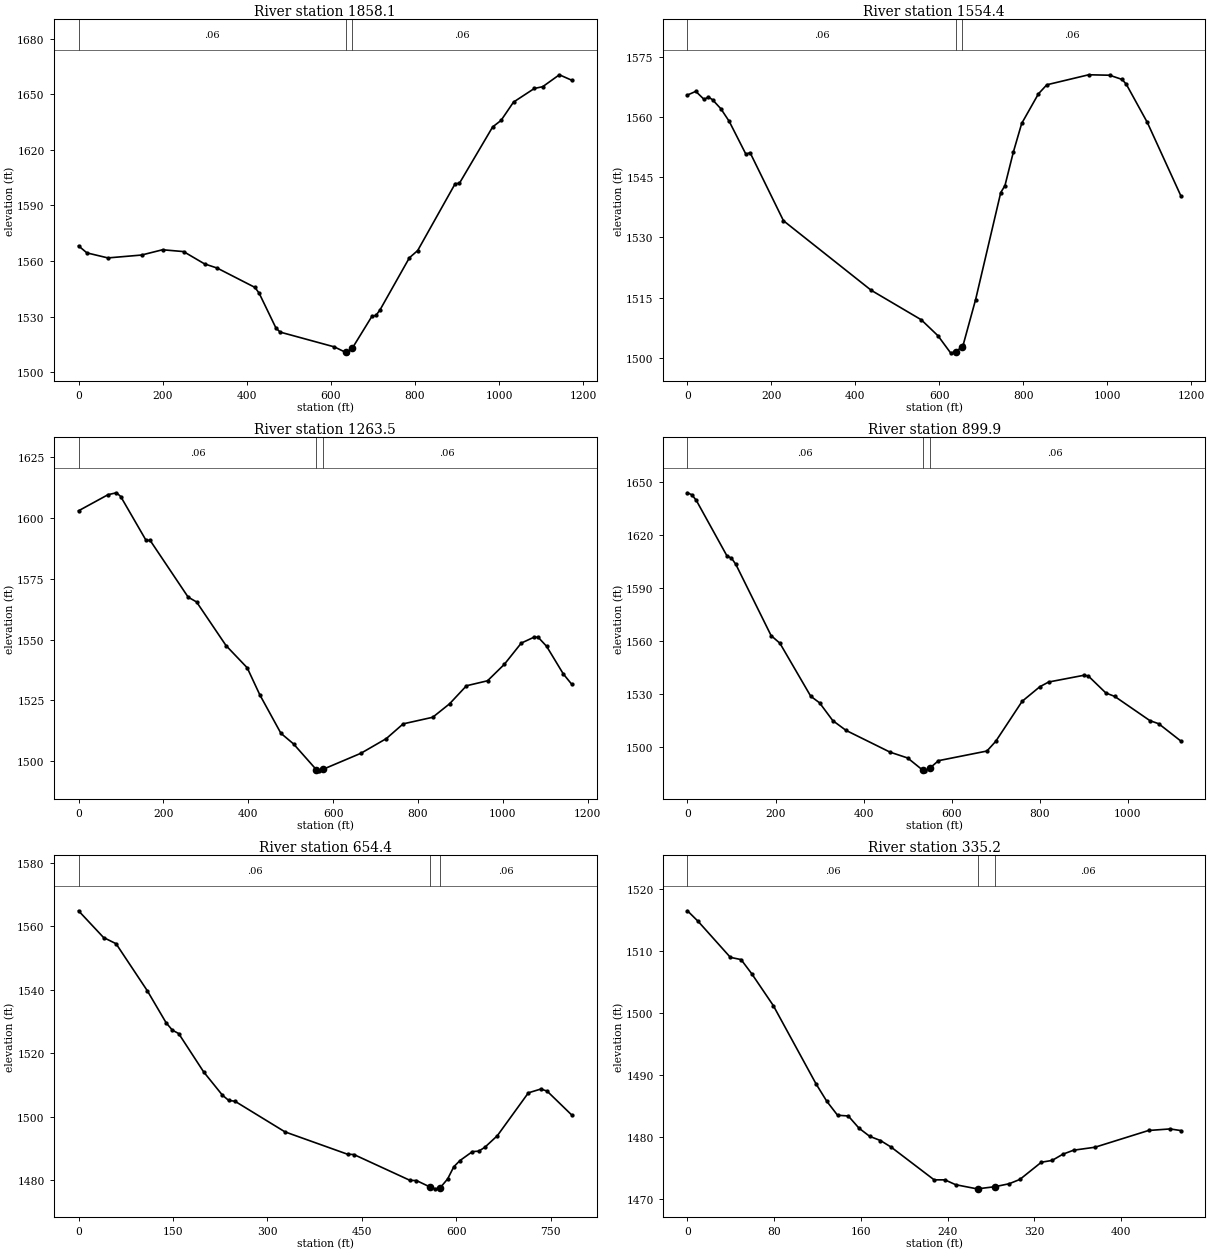
Type RM Length L Ch R = 1 ,1858.1  ,300.6,303.7,309.4
XS GIS Cut Line= 3
     1847986.556      309482.973     1847997.864       309972.43
     1847838.054      310637.226
#Sta/Elev= 30
       0 1568.15      20 1564.35    69.9 1561.64   149.9 1563.19   199.8 1566.04
   249.8 1565.06   299.8 1558.41   329.7 1556.17   419.6 1545.72   429.6 1542.59
   469.6 1523.78   479.6 1521.59   608.5 1513.61   635.8  1510.6   638.2  1510.4
   650.8 1512.77   697.7 1530.07   707.6 1530.62   717.5 1533.76   786.9 1561.71
   806.7 1565.63   895.9 1601.74   905.8 1601.88     985 1632.36  1004.9 1635.85
  1034.6 1645.76  1084.1 1653.11    1104 1654.07  1143.6  1660.5  1173.3 1657.53
#Mann= 3 , 0 , 0
       0     .06       0   635.8    .045       0   650.8     .06       0
Bank Sta=635.8,650.8
XS Rating Curve= 0 ,0
Exp/Cntr=0.3,0.1

Type RM Length L Ch R = 1 ,1554.4  ,286.7,290.7,292.2
XS GIS Cut Line= 3
     1847906.409      309467.371     1847672.118      310069.758
     1847426.084      310537.262
#Sta/Elev= 30
       0 1565.54    19.9 1566.46    39.8 1564.44    49.7 1565.06    59.7 1564.38
    79.6 1562.12    99.4 1558.99   139.2 1550.78   149.2 1551.16   228.7 1534.16
   437.5 1516.81   556.8 1509.44   596.6 1505.45   626.5 1501.19   638.8  1501.4
   653.8 1502.76   656.3 1503.06   686.2  1514.5     746  1541.2     756 1542.92
   775.9 1551.26   795.9 1558.46   835.7 1565.84   855.7  1568.1   955.4  1570.6
  1005.2 1570.49  1035.1 1569.43  1045.1 1568.21  1094.9 1558.72  1174.6 1540.44
#Mann= 3 , 0 , 0
       0     .06       0   638.8    .045       0   653.8     .06       0
Bank Sta=638.8,653.8
XS Rating Curve= 0 ,0
Exp/Cntr=0.3,0.1

Type RM Length L Ch R = 1 ,1263.5  ,375.7,363.5,351.3
XS GIS Cut Line= 2
     1847810.151      309359.963     1847199.028      310349.114
#Sta/Elev= 30
       0 1602.93    69.6 1609.56    89.4 1610.34    99.4 1608.81     159 1590.83
   168.9 1590.73   258.4 1567.44   278.2 1565.47   347.8  1547.5   397.5 1538.42
   427.3 1527.28     477 1511.48   506.8  1507.1   560.3 1496.56   566.4 1496.04
   575.3  1496.6   665.8 1503.28   725.4 1509.29   765.2 1515.35   834.8 1518.06
   874.5 1523.59   914.3 1531.01     964 1533.06  1003.7 1539.84  1043.5 1548.55
  1073.3 1550.96  1083.2 1550.97  1103.1 1547.26  1142.8 1535.82  1162.7 1531.57
#Mann= 3 , 0 , 0
       0     .06       0   560.3    .045       0   575.3     .06       0
Bank Sta=560.3,575.3
XS Rating Curve= 0 ,0
Exp/Cntr=0.3,0.1

Type RM Length L Ch R = 1 ,899.9   ,246.3,245.6,244.1
XS GIS Cut Line= 2
     1847163.586      309282.816     1847145.619       310402.87
#Sta/Elev= 30
       0 1644.15      10 1643.01      20 1639.91      90 1608.29     100 1607.14
     110 1603.56     190 1563.25     210 1558.92     280  1528.9     300 1525.18
   330.1 1515.08   360.1 1509.56   460.1 1497.23   500.1 1493.92     535 1486.89
   540.1 1486.64     550 1488.09   570.1  1492.4   680.1 1497.86   700.1 1503.36
   760.1 1526.04   800.1 1534.26   820.2 1536.95   900.2 1540.77   910.2 1540.39
   950.2 1530.74   970.2 1528.81  1050.2 1515.07  1070.2 1513.32  1120.2 1503.56
#Mann= 3 , 0 , 0
       0     .06       0     535    .045       0     550     .06       0
Bank Sta=535,550
XS Rating Curve= 0 ,0
Exp/Cntr=0.3,0.1

Type RM Length L Ch R = 1 ,654.4   ,340.4,318.7,281
XS GIS Cut Line= 3
     1846902.896      309320.189     1846917.707      309886.244
     1846929.373      310102.874
#Sta/Elev= 30
       0  1564.9    39.7 1556.47    59.6 1554.51   109.3 1539.64   139.1 1529.56
     149 1527.24     159 1526.17   198.7 1514.06   228.5 1506.72   238.4 1505.08
   248.4 1504.81   327.8 1495.15   427.2 1488.09   437.1 1488.01   526.5 1479.83
   536.4 1479.81   558.7  1477.7   566.2 1477.18   573.7 1477.41     586  1480.3
   595.8 1484.15   605.7 1486.12   625.4 1488.93   635.3 1489.06   645.1 1490.29
   664.9 1493.94   714.2 1507.47   733.9 1508.66   743.8 1508.03   783.2 1500.44
#Mann= 3 , 0 , 0
       0     .06       0   558.7    .045       0   573.7     .06       0
Bank Sta=558.7,573.7
XS Rating Curve= 0 ,0
Exp/Cntr=0.3,0.1

Type RM Length L Ch R = 1 ,335.2   ,245.5,231.9,246.6
XS GIS Cut Line= 2
      1846639.71      309508.202     1846660.811      309962.838
#Sta/Elev= 30
       0 1516.46     9.9 1514.75    39.6 1508.95    49.5 1508.59    59.4 1506.29
    79.2 1501.18   118.7 1488.53   128.6 1485.73   138.5 1483.49   148.4 1483.37
   158.3  1481.4   168.2 1480.08   178.1 1479.41     188 1478.34   227.6 1473.07
   237.5 1473.07   247.4 1472.29   267.1 1471.62   268.5 1471.64   283.5 1471.96
   296.8 1472.44   306.7 1473.14   326.5 1475.91   336.4  1476.2   346.3  1477.2
   356.2 1477.85     376 1478.33   425.4 1481.03   445.2 1481.28   455.1 1481.02
#Mann= 3 , 0 , 0
       0     .06       0   268.5    .045       0   283.5     .06       0
Bank Sta=268.5,283.5
XS Rating Curve= 0 ,0
Exp/Cntr=0.3,0.1

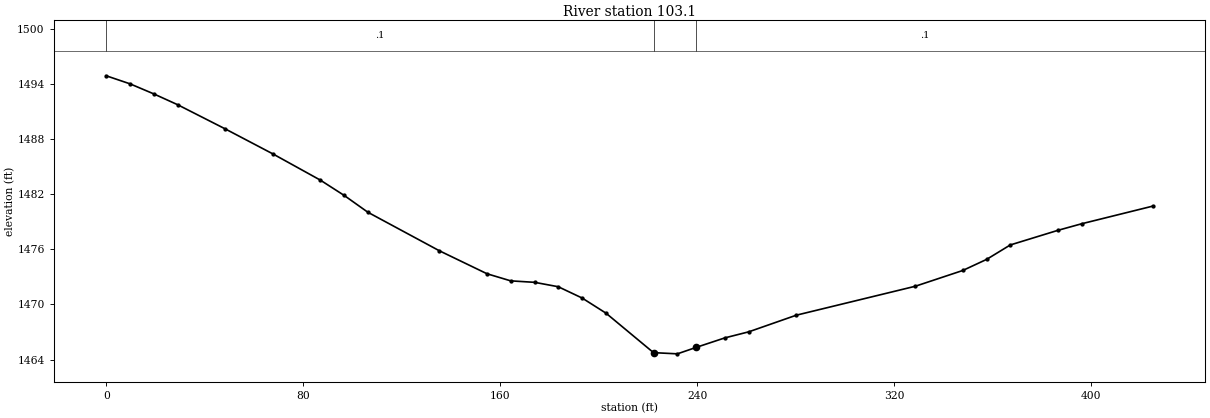
Type RM Length L Ch R = 1 ,103.1   ,107.4,103,98.6
XS GIS Cut Line= 3
      1846279.07      309744.152     1846453.635       309847.74
     1846653.138      309945.574
#Sta/Elev= 29
       0 1494.91     9.7 1494.03    19.3 1492.94      29 1491.76    48.3 1489.13
    67.7  1486.4      87 1483.54    96.7 1481.87   106.3 1480.04   135.3 1475.85
   154.7 1473.34   164.3 1472.57     174 1472.41   183.6 1471.93   193.3  1470.7
     203 1469.05   222.3 1464.75     232 1464.62   239.7 1465.33   251.3 1466.36
     261 1467.02   280.3 1468.83   328.6 1471.98   347.9  1473.7   357.6 1474.91
   367.2 1476.48   386.5 1478.07   396.2 1478.79   425.2 1480.72
#Mann= 3 , 0 , 0
       0      .1       0   222.3    .045       0   239.7      .1       0
Bank Sta=222.3,239.7
XS Rating Curve= 0 ,0
Exp/Cntr=0.3,0.1

Chan Stop Cuts=-1
Use User Specified Reach Order=0
Composite Channel Slope=5